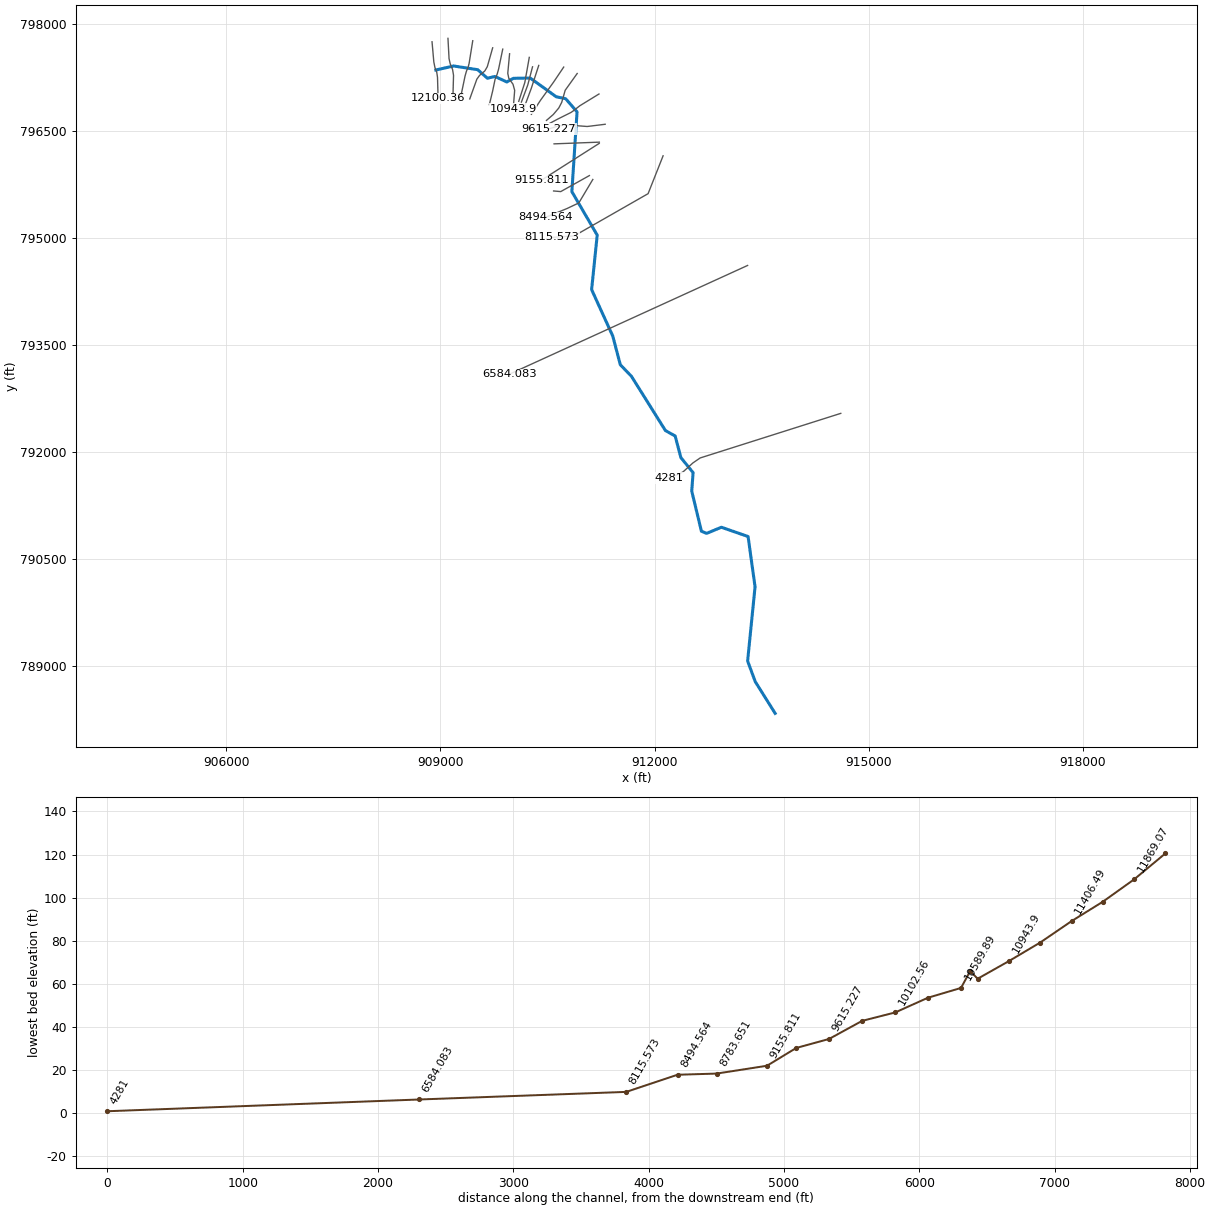
--- 12023_ras.prj (project) ---

Proj Title=12023
Current Plan=p01
Default Exp/Contr=0.3,0.1
English Units
Geom File=g01
Flow File=f01
Plan File=p01
Y Axis Title=Elevation
X Axis Title(PF)=Main Channel Distance
X Axis Title(XS)=Station
BEGIN DESCRIPTION:
RFD model 12023 exported to HEC-RAS
END DESCRIPTION:

--- 12023_ras.p01 (plan) ---

Plan Title=Plan 01
Program Version=4.10
Short Identifier=Plan 01
Geom File=g01
Flow File=f01
Subcritical Flow
Calc Critical at every XS
Secant Critical Depth

--- 12023_ras.f01 (steady flow) ---

Flow Title=Flow 01
Program Version=5.01
Number of Profiles= 6
Profile Names=10yr,25yr,50yr,100yr,100plus,500yr
River Rch & RM=12023,20,12100.36
  155.77  245.89  328.99  403.63  589.31 1022.31
River Rch & RM=12023,20, 10943.9
   164.7  260.13   348.2  427.35  623.93  1074.4
River Rch & RM=12023,20,10712.61
  241.47  381.65  511.25  627.53  916.19 1494.02
River Rch & RM=12023,20,10589.89
  261.57  413.63  554.33  680.57  993.63 1602.57
River Rch & RM=12023,20,10346.22
  266.48  421.52  565.01  693.79 1012.93 1629.78
River Rch & RM=12023,20,10102.56
  282.53  447.31  599.96  737.07 1076.13 1718.53
River Rch & RM=12023,20,9858.891
  286.93   454.4  609.59  749.02 1093.57 1742.98
River Rch & RM=12023,20,9615.227
  290.99  460.93  618.44  759.98 1109.57 1765.27
River Rch & RM=12023,20,9371.561
   298.3  472.69   634.4  779.77 1138.46 1805.52
River Rch & RM=12023,20,9155.811
  307.31  487.23  654.16  804.29 1174.26 1855.34
River Rch & RM=12023,20,8783.651
  334.89  531.81  714.83  879.67 1284.32 2007.55
River Rch & RM=12023,20,8494.564
  353.46  561.94  755.92  930.83 1359.01 2110.31
River Rch & RM=12023,20,8115.573
  358.17  569.62  766.42  943.93 1378.14 2136.63
River Rch & RM=12023,20,6584.083
  758.17 1217.71 1650.12 2043.19 2983.06  4193.1
River Rch & RM=12023,20,    4281
  829.15 1334.65 1811.32 2245.59 3278.57 4559.65
Boundary for River Rch & Prof#=12023,20,1
Up Type= 0
Dn Type= 2
Boundary for River Rch & Prof#=12023,20,2
Up Type= 0
Dn Type= 2
Boundary for River Rch & Prof#=12023,20,2
Up Type= 0
Dn Type= 2
Boundary for River Rch & Prof#=12023,20,2
Up Type= 0
Dn Type= 2
Boundary for River Rch & Prof#=12023,20,2
Up Type= 0
Dn Type= 2
Boundary for River Rch & Prof#=12023,20,2
Up Type= 0
Dn Type= 2

--- 12023_ras.g01 (geometry) ---

Geom Title=12023
Program Version=4.10

River Reach=12023,20
Reach XY= 30
908937.285158574797355.607997729909185.956764045797412.340404515
909522.795697036797360.220492761909659.475180061797240.798788869
909765.027764707797265.149760626909931.165234237797187.842296627
910022.879509748797239.368530766910258.886467695797242.814714303
910624.293326917796980.032988991910755.018040151796953.882788793
910914.740262331796768.986955468910841.992856357795650.547693163
911197.036847029795041.069079898911118.733317881794276.907962412
911415.203038009793625.797776426911520.209012363793224.390601298
911676.459012359793061.630184626 912152.37972996792301.167511063
912288.665592435792225.060832719912368.793611915 791922.17361347
912539.896325472791711.086179689912520.869313303791453.511261027
912656.285979986790889.709177696912729.202646586790859.761261043
912936.233896587790945.698761053913309.931813271 790815.49042771
913407.588063271 790111.06334435913303.421396613789070.698761018
913410.192229957788781.636261035913688.838063271788336.323761052

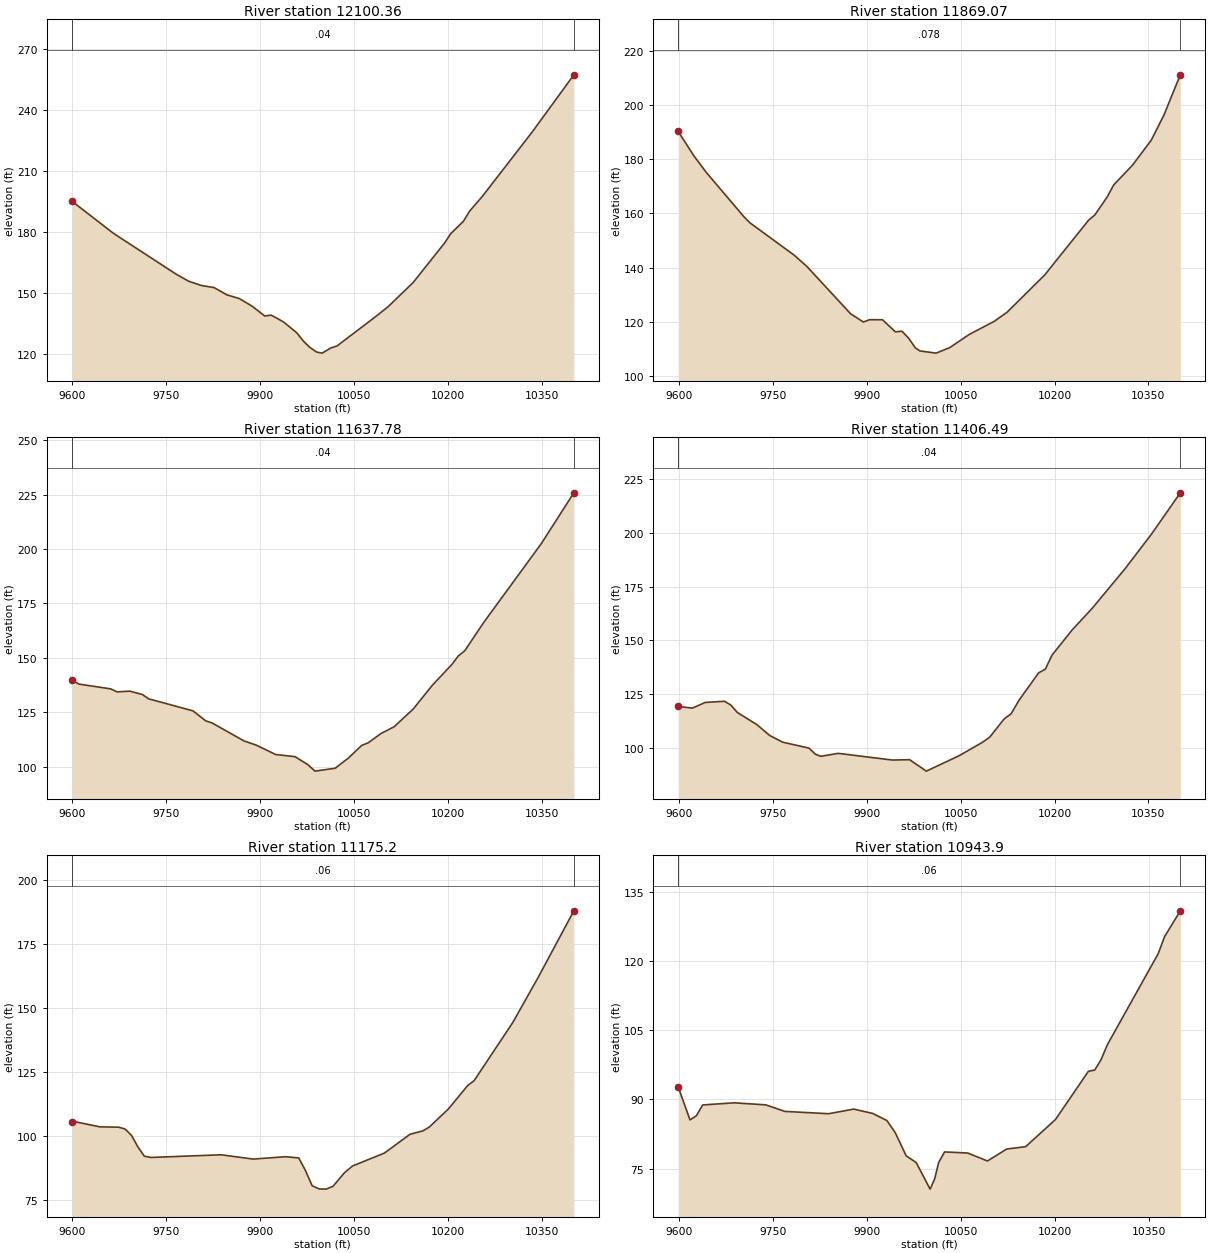
Type RM Length L Ch R = 1 ,12100.36,231.291900,231.291900,231.291900
XS GIS Cut Line= 6
908883.869038325 797751.54346128908909.010460903797468.441669785
908924.382328277797391.233029267908950.104934277 797323.86685841
908960.487450121797253.683135975908969.132375823796958.610677651
#Sta/Elev= 30
9599.057195.30059665.666179.42199765.999159.29599786.148155.81949806.297153.7691
9826.446152.73489846.595149.20689866.744147.33369886.919  143.639907.218138.7844
9917.368139.19729927.247137.60169937.785135.71689958.313130.54269968.751126.4819
9979.296123.33349990.097121.0428    9999120.509910012.27122.979510022.85124.0715
10083.87138.354410104.08143.291310144.25155.225310194.42174.648810204.43179.3219
10224.46185.312810234.47190.379510254.48197.491410334.49229.296310400.92257.3861
#Mann= 3 , 0 , 0
9599.057    0.04       09599.057    0.04       010400.92    0.04       0
#XS Ineff= 2 , 0
       0                               0
Bank Sta=9599.057,10400.92
Exp/Cntr=0.3,0.1

Type RM Length L Ch R = 1 ,11869.07,231.291900,231.291900,231.291900
XS GIS Cut Line= 6
 909106.98224045797799.826344905909122.286620559797514.347923762
909138.538494815797442.306215195909171.519249698797362.608418513
909184.895476655797281.696236167909177.511796235797008.886930084
#Sta/Elev= 30
9599.058190.26759623.884181.29469643.884175.1304  9703.9158.79339713.907 156.473
 9784.01144.64429804.067140.55299874.474122.95429894.726  119.949904.906120.8006
9925.266120.76269945.953116.29379956.326116.56139966.937113.98879977.637110.4253
9985.018109.268810010.93108.456410032.48110.463510063.57115.307610104.14120.2411
 10124.3123.558510184.42 137.32210254.43157.491410264.44159.447210284.46166.1856
10294.47170.500510324.52177.793410354.63187.066310374.71196.265110400.92211.1387
#Mann= 3 , 0 , 0
9599.058   0.078       09599.058   0.078       010400.92   0.078       0
#XS Ineff= 2 , 0
       0                               0
Bank Sta=9599.058,10400.92
Exp/Cntr=0.3,0.1

Type RM Length L Ch R = 1 ,11637.78,231.291900,231.291900,231.291900
XS GIS Cut Line= 6
909454.089941501 797766.49752506909403.199244982797448.690745686
909392.176678657797405.474487968909364.445328488797334.735830899
909346.710200091797272.648210685909286.689544749796983.968972019
#Sta/Elev= 30
 9599.05139.84289610.677138.00939661.241 135.8169671.353134.44539691.579134.7794
9711.804133.25079721.917131.24489792.706 125.7319813.008121.14619823.159120.1899
9873.916111.96479894.219109.94929924.735 105.6989955.696104.71259976.745100.9304
9987.45598.0794110019.7199.4015710041.23104.153510062.03109.860210072.43 111.071
10093.23115.386210113.92118.446710144.66126.6368 10175.4137.644310206.14147.0114
10216.39150.927510226.63153.274110257.21166.382710348.94 202.44610400.96225.7779
#Mann= 3 , 0 , 0
 9599.05    0.04       0 9599.05    0.04       010400.96    0.04       0
#XS Ineff= 2 , 0
       0                               0
Bank Sta=9599.05,10400.96
Exp/Cntr=0.3,0.1

Type RM Length L Ch R = 1 ,11406.49,231.291800,231.291800,231.291800
XS GIS Cut Line= 6
909733.151932539797666.974385599909657.612506492797401.705093756
909622.278321419797341.677513172909548.908412183797279.537008272
909511.517608384797227.116280438909412.111182964 796950.14395825
#Sta/Elev= 30
9599.135119.14999621.699118.39789642.235121.0404 9673.04121.58319683.308119.7776
9693.594116.35459724.602110.74599745.275105.63969766.053102.52889807.89799.78715
9818.358 96.91069826.78895.968919854.68197.333379941.06894.224499968.62594.38595
9995.31589.0660310047.6596.2224310085.02102.496910096.78104.954210119.55113.3604
 10130.7115.764210143.42122.097910174.58134.784910185.36136.541610196.14143.1203
10228.35154.849110260.01164.795710312.54183.245410354.19199.119210400.89218.6107
#Mann= 3 , 0 , 0
9599.135    0.04       09599.135    0.04       010400.89    0.04       0
#XS Ineff= 2 , 0
       0                               0
Bank Sta=9599.135,10400.89
Exp/Cntr=0.3,0.1

Type RM Length L Ch R = 1 , 11175.2,231.291900,231.291900,231.291900
XS GIS Cut Line= 6
909874.112359407797648.560130992909816.047177914 797368.71403871
909795.844614654797297.388028354909767.297621867797227.631878892
909733.054026982797062.278163547909686.566077446796870.205730373
#Sta/Elev= 30
9599.051105.21439602.687105.57769643.904103.50359674.178103.37189684.391102.6229
9694.604100.11189704.81795.59911 9715.0392.037669725.24391.537779837.58692.57811
9888.71890.907369940.68591.824349961.55291.357139972.28286.428939983.01380.47386
 9994.0879.23853 10005.279.15578 10016.280.2425710034.4785.5383810047.3788.19486
10098.4393.2524210139.28100.599110159.71101.916910169.92103.388910200.55110.4887
 10231.4119.663810241.69121.565610303.42 144.29310344.58162.194710400.95187.9569
#Mann= 3 , 0 , 0
9599.051    0.06       09599.051    0.06       010400.95    0.06       0
#XS Ineff= 2 , 0
       0                               0
Bank Sta=9599.051,10400.95
Exp/Cntr=0.3,0.1

Type RM Length L Ch R = 1 , 10943.9,231.291900,231.291900,231.291900
XS GIS Cut Line= 6
909969.970384894797583.539869148909944.617421737797309.850154023
909958.622026962797240.476988634910017.656617608797156.490589536
910041.156549872797070.948159669 910020.70803429 796810.39016851
#Sta/Elev= 30
9599.24892.715349618.02985.575529628.15986.457819638.28888.814759688.83289.27744
9739.19788.828439769.33787.415379839.44986.910059879.484 87.91449909.71186.96923
9932.30885.438919945.59482.814659963.13677.767599979.133 76.3066 10001.370.53396
 10008.672.75683   1001576.3287510024.4378.6082610061.2178.3779410092.8976.64724
10123.5479.2390610153.8979.7550810201.4785.6557110254.0796.1259410264.0896.38715
10274.1398.6249710284.21101.869410365.39121.6476 10375.6125.350410400.74130.9674
#Mann= 3 , 0 , 0
9599.248    0.06       09599.248    0.06       010400.74    0.06       0
#XS Ineff= 2 , 0
       0                               0
Bank Sta=9599.248,10400.74
Exp/Cntr=0.3,0.1

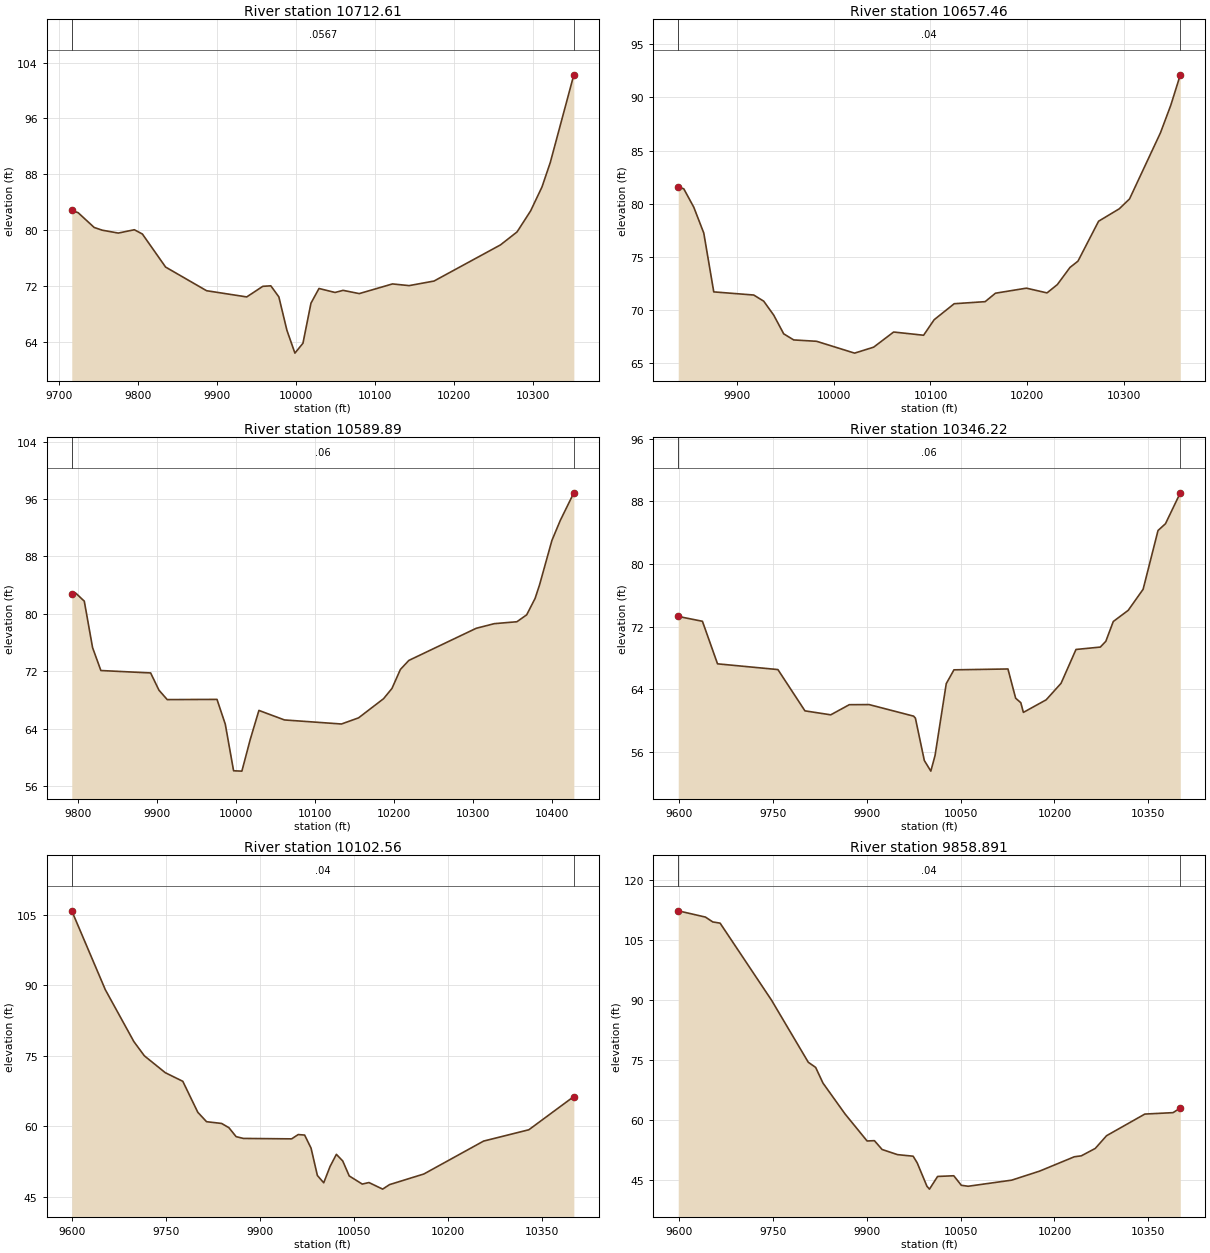
Type RM Length L Ch R = 1 ,10712.61,55.151600,55.151600,55.151600
XS GIS Cut Line= 3
910245.795400486797532.941692429910182.861372708797179.209053541
910098.225956041796916.622247985
#Sta/Elev= 30
9716.296 82.80539724.36282.472329744.67780.356029754.83479.965989775.14879.55329
9795.462   80.039805.61979.418719835.016 74.67939886.87571.28824 9937.6670.40029
9957.97471.918799968.13171.992139978.28870.403319988.44565.630239998.60262.34259
10008.7663.7586410018.9269.5062110029.0771.6112110049.3971.0385410059.5471.34127
10080.0170.8755810122.0372.2629910143.0572.0191610174.5772.6751310258.6277.85416
10279.6379.7169510296.7982.7345310311.1586.1588210321.6689.6691210351.47102.2382
#Mann= 3 , 0 , 0
9716.296  0.0567       09716.296  0.0567       010351.47  0.0567       0
#XS Ineff= 2 , 0
       0                10275.22       0
Bank Sta=9716.296,10351.47
Exp/Cntr=0.3,0.1

Type RM Length L Ch R = 1 ,10657.46,67.574900,67.574900,67.574900
XS GIS Cut Line= 3
910291.368317152797400.563220207910224.094011597797144.486831318
910135.118317152796905.771553541
#Sta/Elev= 30
9839.00281.570669844.754 81.39559855.093 79.66259865.43277.229969875.77271.68391
9917.12971.388779927.46870.807349937.80869.495299948.14767.731799958.48667.15817
9982.13367.0294310021.49 65.9143 10041.266.4753810061.8867.90283 10092.967.59973
10103.7769.0571210124.5670.5694510156.58 70.764110167.2571.5599410199.2772.03529
10220.6171.5891510231.2872.3713710244.3473.9843510252.6374.5802510273.9778.34191
10295.3279.5094310305.9980.44342   1033886.6759310348.6889.2724710358.5392.13556
#Mann= 3 , 0 , 0
9839.002    0.04       09839.002    0.04       010358.53    0.04       0
#XS Ineff= 2 , 0
       0                10256.37       0
Bank Sta=9839.002,10358.53
Exp/Cntr=0.3,0.1

Type RM Length L Ch R = 1 ,10589.89,243.665000,243.665000,243.665000
XS GIS Cut Line= 3
910378.173872708797420.094470207910274.007206041797098.913914652
910169.840539375796818.965997985
#Sta/Elev= 30
9791.67782.825559797.03382.850659807.54681.761529818.05875.286339828.57172.09838
9891.64871.760699902.16169.364259912.673 68.0474 9975.7568.076239986.26364.62085
9996.77658.1304310007.2958.08207 10017.862.4628210028.8766.5390310061.2865.21291
 10133.5 64.648210155.1665.5031310186.8568.1715110197.5269.6056210208.1972.24637
10218.8673.5027510304.2277.9805710327.2178.6272910355.8878.8957610368.2479.85706
10378.9182.1453910384.5684.0318510400.2590.2292310410.9293.0287310428.03 96.8561
#Mann= 3 , 0 , 0
9791.677    0.06       09791.677    0.06       010428.03    0.06       0
#XS Ineff= 2 , 0
       0                10213.58       0
Bank Sta=9791.677,10428.03
Exp/Cntr=0.3,0.1

Type RM Length L Ch R = 1 ,10346.22,243.665000,243.665000,243.665000
XS GIS Cut Line= 6
910728.033174502797397.065397189910584.991101561797184.578240537
910500.965439101797067.826231829910499.798871765797066.201694772
 910400.93632381796928.788283267910275.565807034796735.125301211
#Sta/Elev= 30
9599.00773.305199637.66172.685539661.77167.249159758.20966.516029801.41861.24045
9842.59260.733499872.25962.028349903.91862.041979974.974 60.56569977.84160.30849
9992.09354.8982510002.48 53.539810009.2255.5305310027.1264.7200510039.44 66.4821
10125.67 66.591810137.9962.85226 10146.262.2841610150.3161.0441310186.7162.65042
10210.53 64.765310234.3669.0838710273.2169.3897110282.0170.1279310293.9272.65877
10317.7474.0821210341.5776.7766810365.3984.2835110377.31 85.154410400.9889.09848
#Mann= 3 , 0 , 0
9599.007    0.06       09599.007    0.06       010400.98    0.06       0
#XS Ineff= 2 , 0
       0                10062.66       0
Bank Sta=9599.007,10400.98
Exp/Cntr=0.3,0.1

Type RM Length L Ch R = 1 ,10102.56,243.664900,243.664900,243.664900
XS GIS Cut Line= 6
 910916.68239795797306.835773887910748.859769653797071.975457208
910699.787963674796901.839673884  910658.9218223796823.427091875
 910582.69689922796732.640790418910486.545393171796649.216738379
#Sta/Elev= 30
 9599.07105.80519652.66589.044229698.23678.029539714.96875.008599748.43171.41666
9776.37869.587939800.33263.008199814.30561.00879 9838.3560.635869850.00759.73622
9861.55257.829919873.09757.45321 9950.1457.362399960.66658.274789970.92658.16816
9981.18655.392189991.32449.5807110001.4248.0291910011.5451.4921210021.6554.07275
10031.7752.6663910042.1649.4838310062.9447.75691 10073.748.0800510095.5546.68394
 10106.547.6413210161.3849.9001510256.7356.8893510329.02 59.298810400.8566.35171
#Mann= 3 , 0 , 0
 9599.07    0.04       0 9599.07    0.04       010400.85    0.04       0
#XS Ineff= 2 , 0
       0                10024.01       0
Bank Sta=9599.07,10400.85
Exp/Cntr=0.3,0.1

Type RM Length L Ch R = 1 ,9858.891,243.665000,243.665000,243.665000
XS GIS Cut Line= 6
911221.986488852797019.552185166910954.295562058796855.040480812
910856.096407024796778.480603373910827.032313075796759.093929546
910647.331242382796669.487076574910534.974951333796609.531604099
#Sta/Elev= 30
9599.031112.21149642.443110.65279654.181 109.4429665.918 109.1359748.08189.91416
9806.76874.436299818.50673.153739830.243 69.23919865.455 61.54529900.66854.80179
9912.40554.878549924.65352.679539949.22451.396039974.25351.003959980.67449.35136
9996.30143.5021310000.3142.79165 10013.345.9570910039.1546.1247210051.1743.74733
10062.1343.5080710131.5745.0284610176.0747.2741110231.6950.8612610242.8251.09502
10265.0752.9376610283.1356.1135810344.2561.5113410389.3461.8703210400.95 63.0215
#Mann= 3 , 0 , 0
9599.031    0.04       09599.031    0.04       010400.95    0.04       0
#XS Ineff= 2 , 0
       0                10112.03       0
Bank Sta=9599.031,10400.95
Exp/Cntr=0.3,0.1

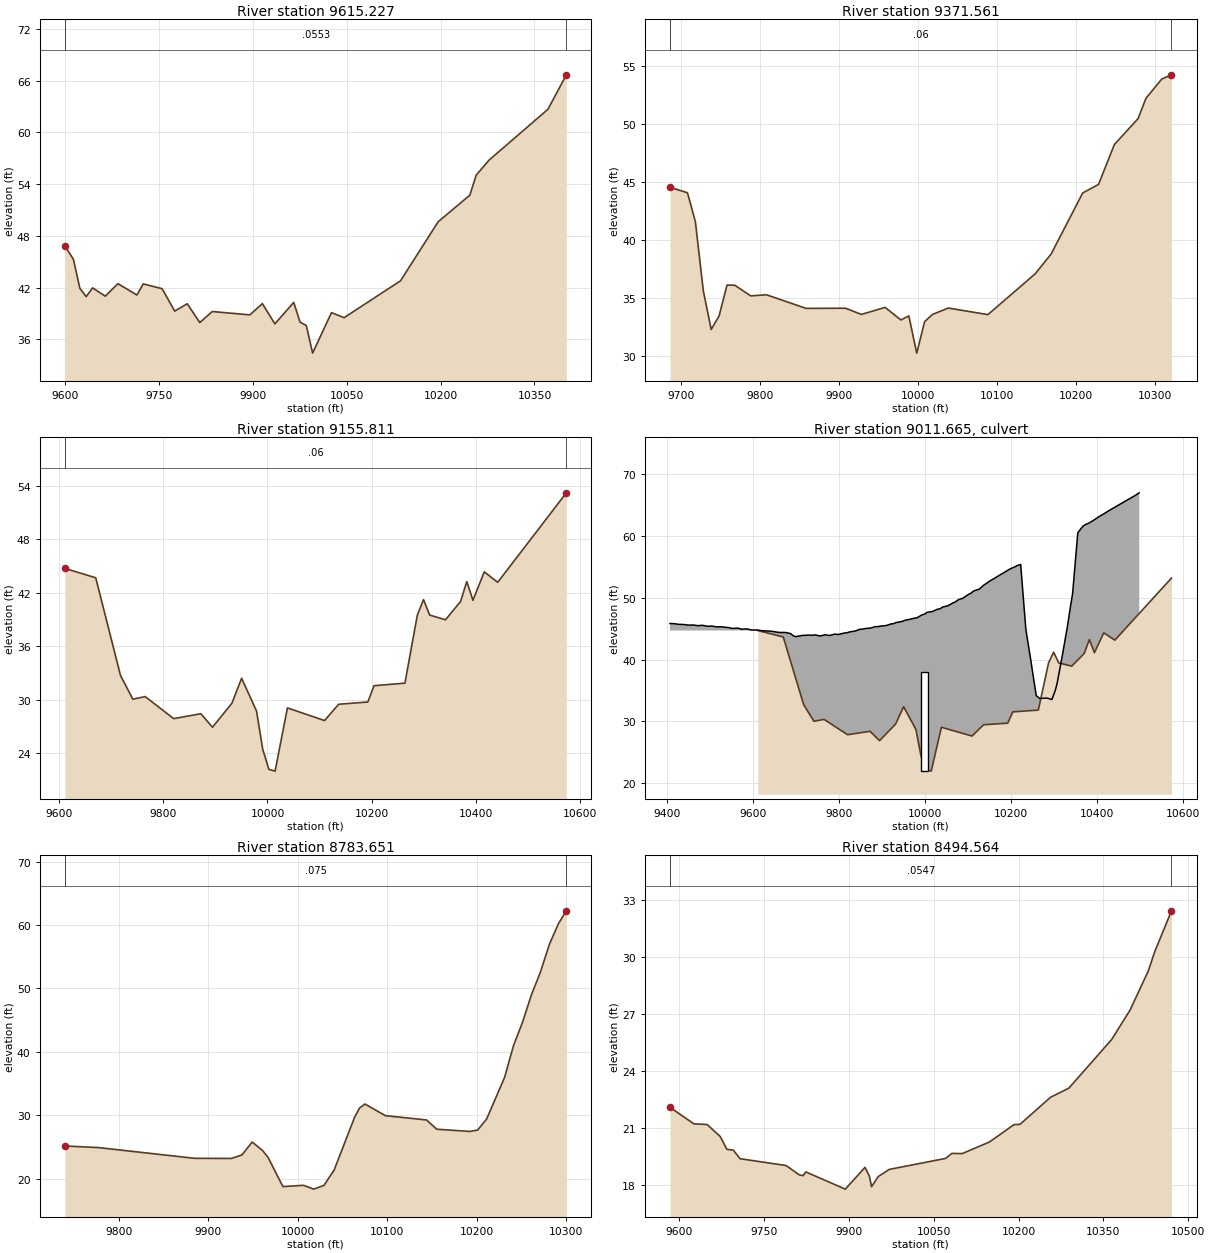
Type RM Length L Ch R = 1 ,9615.227,243.665000,243.665000,243.665000
XS GIS Cut Line= 6
911308.524747992796595.199935577911056.855576569796563.919760895
 910804.68843117796583.591790966910723.674161096796581.709241245
910638.504212932 796567.42062217910517.169651723796529.026689123
#Sta/Elev= 30
9599.05746.866999612.833 45.26889623.01941.925749633.20540.959679643.391 41.9784
9663.70441.013869683.93242.466429714.27441.146389724.38842.436019754.591 41.8798
9774.694 39.28219794.789 40.13559814.81337.953179834.83739.232659894.87438.84244
9914.88240.153769934.89337.801269965.04740.290939975.09838.008199985.14937.61116
  9995.2  34.409 10025.439.1030310045.5438.52114 10135.842.7958910195.9449.63801
10246.58 52.722710256.7855.0456110277.2456.7838510371.4562.6816410400.9466.68186
#Mann= 3 , 0 , 0
9599.057  0.0553       09599.057  0.0553       010400.94  0.0553       0
#XS Ineff= 2 , 0
       0                10096.48       0
Bank Sta=9599.057,10400.94
Exp/Cntr=0.3,0.1

Type RM Length L Ch R = 1 ,9371.561,215.750100,215.750100,215.750100
XS GIS Cut Line= 2
911227.108614208796344.525761451910592.754462785796320.546738545
#Sta/Elev= 30
9686.45544.501149708.57944.034079718.58641.543279728.593  35.596  9738.632.24287
9748.60733.408899758.61536.074879768.62236.054379788.63635.14154 9808.6535.23654
9858.68634.063959908.72234.076919928.73633.540429958.75734.149229978.77233.06335
9988.77933.415769998.78630.2058510008.7932.92368 10018.8 33.542810038.8134.09321
10088.8533.5241510148.8937.0528410168.9138.7518110208.9444.0194410228.95 44.7525
10248.9648.1912310278.9950.4263210288.9952.1822210309.0153.8395610321.2654.20038
#Mann= 3 , 0 , 0
9686.455    0.06       09686.455    0.06       010321.26    0.06       0
#XS Ineff= 2 , 0
       09907.625                       0
Bank Sta=9686.455,10321.26
Exp/Cntr=0.3,0.1

Type RM Length L Ch R = 1 ,9155.811,372.160300,372.160300,372.160300
XS GIS Cut Line= 2
911224.928703035796327.086472065910414.001746577795810.447523999
#Sta/Elev= 30
9611.55944.72805 9670.7643.672519718.18832.712629741.90230.036079765.616  30.331
9820.16427.856439872.32928.406519894.60826.89164 9931.8329.580169950.441 32.3855
9979.04328.71385  9990.924.4264810002.7622.1578710014.6121.9604310038.3329.06163
10109.4727.6394710136.5529.4696410192.38 29.721810204.3331.5528510263.6131.84128
10287.3339.4715810299.1841.2197910311.0439.4856210341.2738.9555810370.3241.01188
10382.1843.2467710394.0441.1449310415.7244.3456810441.4743.1630510573.0853.21453
#Mann= 3 , 0 , 0
9611.559    0.06       09611.559    0.06       010573.08    0.06       0
#XS Ineff= 2 , 0
       09952.768        10045.67       0
Bank Sta=9611.559,10573.08
Exp/Cntr=0.3,0.1

Type RM Length L Ch R = 2 ,9011.665,,,
Bridge Culvert--1,0,-1,-1, 0
Deck Dist Width WeirC Skew NumUp NumDn MinLoCord MaxHiCord MaxSubmerge Is_Ogee
30.08,312,2.6,0,152,152, , , 0.95, 0, 0,0,,
 9407.48 9415.50 9418.45 9426.84 9438.19 9439.62 9449.53 9460.79 9460.88 9472.22
 9481.96 9483.57 9494.91 9503.13 9506.26 9517.61 9524.30 9528.95 9540.30 9545.47
 9551.64 9562.99 9566.64 9574.33 9585.68 9587.82 9597.02 9608.37 9608.99 9619.71
 9630.16 9631.06 9642.40 9651.33 9653.75 9665.10 9672.50 9676.44 9687.79 9693.67
 9699.13 9710.48 9714.84 9721.82 9733.17 9736.01 9744.51 9755.86 9757.19 9767.20
 9778.36 9778.55 9789.89 9799.53 9801.24 9812.58 9819.15 9820.46 9824.24 9836.31
 9838.31 9848.38 9856.17 9860.45 9872.52 9874.03 9884.59 9891.89 9896.66 9908.73
 9909.74 9920.80 9927.60 9932.87 9944.94 9945.46 9957.01 9963.31 9969.08 9981.15
 9981.17 9993.22 9999.0310005.2910016.8910017.3610029.4310034.7410041.5010052.60
10053.5710065.6410070.4610077.7110088.3110089.7810101.8510106.1710113.9210124.03
10125.9910138.0610141.8910150.1310159.7410162.2010174.2710177.6010186.3410195.46
10198.4110210.4810213.3110222.5510231.1710234.6210246.6910249.0310258.7610266.89
10270.8310282.9010284.7410294.9710302.6010307.0410319.1110320.4610331.1810338.31
10343.2510355.3210356.1710367.3910374.0310379.4610391.5310391.8910403.6010409.74
10415.6710427.6010427.7410439.8110445.4610451.8810463.3110463.9510476.0210481.17
10488.0910498.09
   45.86   45.83   45.83   45.73   45.69   45.70   45.60   45.62   45.62   45.51
   45.57   45.56   45.41   45.45   45.43   45.30   45.35   45.31   45.21   45.18
   45.06   45.12   45.09   44.93   44.99   44.97   44.80   44.83   44.82   44.71
   44.67   44.65   44.61   44.53   44.48   44.40   44.42   44.40   44.23   43.90
   43.73   43.88   43.93   43.95   43.99   43.94   44.02   43.85   43.85   44.04
   43.92   43.92   44.14   44.09   44.12   44.32   44.39   44.39   44.49   44.62
   44.65   44.91   44.97   45.04   45.11   45.13   45.35   45.37   45.44   45.52
   45.53   45.78   45.85   46.02   46.17   46.17   46.46   46.50   46.63   46.78
   46.78   47.26   47.38   47.68   47.79   47.80   48.18   48.23   48.53   48.71
   48.74   49.21   49.34   49.72   49.96   50.04   50.60   50.74   51.15   51.37
   51.42   52.14   52.31   52.71   53.11   53.21   53.73   53.84   54.22   54.58
   54.72   55.08   55.21   55.43   47.98   44.89   39.67   38.54   34.19   33.72
   33.74   33.79   33.77   33.55   34.95   36.09   40.54   41.11   45.38   48.61
   50.70   60.56   60.63   61.63   61.92   62.06   62.55   62.57   63.12   63.36
   63.61   64.13   64.14   64.63   64.88   65.11   65.58   65.60   66.11   66.31
   66.57   67.02
                                                                                
                                                                                
                                                                                
                                                                                
                                                                                
                                                                                
                                                                                
                                                                                
                                                                                
                                                                                
                                                                                
                                                                                
                                                                                
                                                                                
                                                                                
                
 9407.48 9415.50 9418.45 9426.84 9438.19 9439.62 9449.53 9460.79 9460.88 9472.22
 9481.96 9483.57 9494.91 9503.13 9506.26 9517.61 9524.30 9528.95 9540.30 9545.47
 9551.64 9562.99 9566.64 9574.33 9585.68 9587.82 9597.02 9608.37 9608.99 9619.71
 9630.16 9631.06 9642.40 9651.33 9653.75 9665.10 9672.50 9676.44 9687.79 9693.67
 9699.13 9710.48 9714.84 9721.82 9733.17 9736.01 9744.51 9755.86 9757.19 9767.20
 9778.36 9778.55 9789.89 9799.53 9801.24 9812.58 9819.15 9820.46 9824.24 9836.31
 9838.31 9848.38 9856.17 9860.45 9872.52 9874.03 9884.59 9891.89 9896.66 9908.73
 9909.74 9920.80 9927.60 9932.87 9944.94 9945.46 9957.01 9963.31 9969.08 9981.15
 9981.17 9993.22 9999.0310005.2910016.8910017.3610029.4310034.7410041.5010052.60
10053.5710065.6410070.4610077.7110088.3110089.7810101.8510106.1710113.9210124.03
10125.9910138.0610141.8910150.1310159.7410162.2010174.2710177.6010186.3410195.46
10198.4110210.4810213.3110222.5510231.1710234.6210246.6910249.0310258.7610266.89
10270.8310282.9010284.7410294.9710302.6010307.0410319.1110320.4610331.1810338.31
10343.2510355.3210356.1710367.3910374.0310379.4610391.5310391.8910403.6010409.74
10415.6710427.6010427.7410439.8110445.4610451.8810463.3110463.9510476.0210481.17
10488.0910498.09
   45.86   45.83   45.83   45.73   45.69   45.70   45.60   45.62   45.62   45.51
   45.57   45.56   45.41   45.45   45.43   45.30   45.35   45.31   45.21   45.18
   45.06   45.12   45.09   44.93   44.99   44.97   44.80   44.83   44.82   44.71
   44.67   44.65   44.61   44.53   44.48   44.40   44.42   44.40   44.23   43.90
   43.73   43.88   43.93   43.95   43.99   43.94   44.02   43.85   43.85   44.04
   43.92   43.92   44.14   44.09   44.12   44.32   44.39   44.39   44.49   44.62
   44.65   44.91   44.97   45.04   45.11   45.13   45.35   45.37   45.44   45.52
   45.53   45.78   45.85   46.02   46.17   46.17   46.46   46.50   46.63   46.78
   46.78   47.26   47.38   47.68   47.79   47.80   48.18   48.23   48.53   48.71
   48.74   49.21   49.34   49.72   49.96   50.04   50.60   50.74   51.15   51.37
   51.42   52.14   52.31   52.71   53.11   53.21   53.73   53.84   54.22   54.58
   54.72   55.08   55.21   55.43   47.98   44.89   39.67   38.54   34.19   33.72
   33.74   33.79   33.77   33.55   34.95   36.09   40.54   41.11   45.38   48.61
   50.70   60.56   60.63   61.63   61.92   62.06   62.55   62.57   63.12   63.36
   63.61   64.13   64.14   64.63   64.88   65.11   65.58   65.60   66.11   66.31
   66.57   67.02
                                                                                
                                                                                
                                                                                
                                                                                
                                                                                
                                                                                
                                                                                
                                                                                
                                                                                
                                                                                
                                                                                
                                                                                
                                                                                
                                                                                
                                                                                
                
BR Coef=-1 , 0 , 0 ,, 0 ,,,0.8,-1,,0,
WSPro=,,,, 1 ,,,, 0 ,,,, 0 ,,,,-1 ,-1 ,-1 , 0 , 0 , 0 , 0 , 0
Culvert=2,16,16,312,0.013,0.7,1,8,3,22,10000,18,10000,Culvert #1, 0, 30.08
Culvert Bottom n=0.013
BC Design=,, 0 ,, 0 ,,,,,,

Type RM Length L Ch R = 1 ,8783.651,289.087600,289.087600,289.087600
XS GIS Cut Line= 3
911087.594299118795875.844859197910686.490643236 795651.31400835
910586.214729265795660.033653043
#Sta/Elev= 30
9739.80625.13703 9777.16 24.88329884.84423.187169925.78923.168639937.602 23.7166
9949.06225.756549960.52324.446599966.73423.370659983.443 18.722910006.36 18.9303
10017.8218.3265310029.2818.9149110040.7421.3570310063.6629.70668 10069.131.13266
10075.1231.7546210098.0429.9196910143.8929.2426810155.3527.7826310191.9327.43217
10200.9727.6399410211.0129.3836310231.09 35.946910241.1340.9922610251.1644.66181
 10261.249.0238510271.2452.6068510281.2857.0019610291.3160.2239610300.13 62.2508
#Mann= 3 , 0 , 0
9739.806   0.075       09739.806   0.075       010300.13   0.075       0
#XS Ineff= 2 , 0
       09952.133        10072.36       0
Bank Sta=9739.806,10300.13
Exp/Cntr=0.3,0.1

Type RM Length L Ch R = 1 ,8494.564,378.990200,378.990200,378.990200
XS GIS Cut Line= 4
 911135.55234493795821.347079866910939.360339336795492.180492701
910773.687090167795413.703690463910477.219170602 795291.62866476
#Sta/Elev= 30
9583.30722.098649625.62121.228969648.90421.194929672.18720.562239683.82819.88908
 9695.4719.842269707.11119.392469788.60219.033519811.88518.544339818.76818.49791
9823.52618.697339893.37517.79063  9928.318.93575 9935.9618.473769939.94117.91646
9951.58318.452219971.33218.8309710070.9219.4078510081.9819.6735210100.0819.66017
10148.3720.2731410191.6721.1842110202.4821.2051410256.5522.62976   1028923.11226
 10364.725.6739310397.1427.2205110429.5929.29346 10440.430.2663510470.4432.44931
#Mann= 3 , 0 , 0
9583.307  0.0547       09583.307  0.0547       010470.44  0.0547       0
#XS Ineff= 2 , 0
       09909.858        10076.75       0
Bank Sta=9583.307,10470.44
Exp/Cntr=0.3,0.1

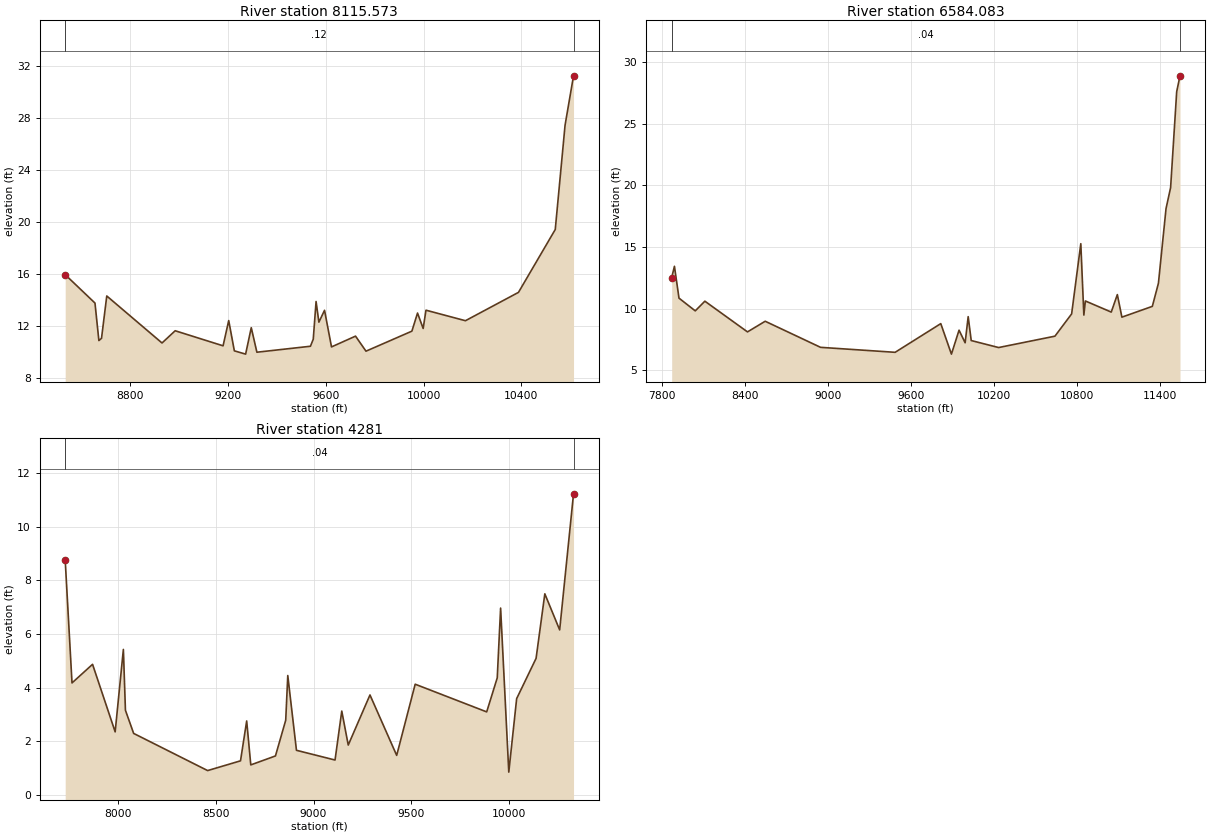
Type RM Length L Ch R = 1 ,8115.573,1531.490000,1531.490000,1531.490000
XS GIS Cut Line= 4
912119.808823946796153.012589594911909.686654269 795622.17763462
910875.664398224795030.517841054910560.481143708 795008.39971793
#Sta/Elev= 30
8535.04115.939028656.78813.756588672.71710.873148683.47211.045378704.98214.30061
8930.83610.68694 8984.6111.627629180.47710.46965 9203.5212.410599226.56310.08356
9272.6489.830527 9295.69 11.86359318.7339.9776889537.63810.435649549.159 10.9766
 9560.6813.875319572.20212.286989595.24413.200939623.786 10.38539721.97911.21364
9764.734 10.05719952.40511.596339975.44712.98894 9998.4911.8031910010.0113.20806
10171.3112.3990510388.1714.5781710538.5319.4113510578.6327.4326110613.2431.22672
#Mann= 3 , 0 , 0
8535.041    0.12       08535.041    0.12       010613.24    0.12       0
#XS Ineff= 2 , 0
       09789.519                       0
Bank Sta=8535.041,10613.24
Exp/Cntr=0.3,0.1

Type RM Length L Ch R = 1 ,6584.083,2303.083300,2303.083300,2303.083300
XS GIS Cut Line= 2
913303.128411077 794615.80303248909963.291819361793089.652536927
#Sta/Elev= 30
7873.27312.500197893.20413.433017926.18810.845998043.6299.8126378113.09610.59909
8420.9448.1052718548.9018.9694978948.683  6.85229487.4176.4475359817.2558.776665
9894.2176.300685 9949.19 8.245169993.1687.22177910015.169.34350710037.157.403747
10235.056.83477510641.857.75819510762.48 9.5656710828.76 15.266710850.749.471012
10861.7410.6159511048.659.71396611092.63 11.133211125.619.302232 11345.510.17876
11389.48 12.056211444.4518.1196311477.4419.8196811521.4127.6081311545.2828.89627
#Mann= 3 , 0 , 0
7873.273    0.04       07873.273    0.04       011545.28    0.04       0
#XS Ineff= 2 , 0
       08860.903                       0
Bank Sta=7873.273,11545.28
Exp/Cntr=0.3,0.1

Type RM Length L Ch R = 1 ,    4281,0.000000,0.000000,0.000000
XS GIS Cut Line= 6
 914608.09767539 792542.22898961912639.305977453791917.263148321
912538.385932885791848.094891818912401.207099941791723.543641101
912329.639287511791685.901779003912198.559548534791635.123835539
#Sta/Elev= 30
7732.2768.7529847767.0014.1765577871.9194.8707287987.3282.3538398029.2955.426027
8039.7873.1580518081.7542.2956918459.4560.9105448627.3241.2740578658.7992.759936
8679.7831.1223948805.6841.4560298858.1422.7868328868.6344.4528728912.9711.666369
9109.9441.3039799144.3313.1280859177.3831.8614749288.3033.7295229424.6961.477016
9519.1224.1291789884.2293.0978259938.0974.3657219955.2926.9669379997.0140.853002
10037.193.59238810136.395.09289110181.037.49766310256.766.15352210327.5811.22441
#Mann= 3 , 0 , 0
7732.276    0.04       07732.276    0.04       010327.58    0.04       0
#XS Ineff= 2 , 0
       09299.142                       0
Bank Sta=7732.276,10327.58
Exp/Cntr=0.3,0.1